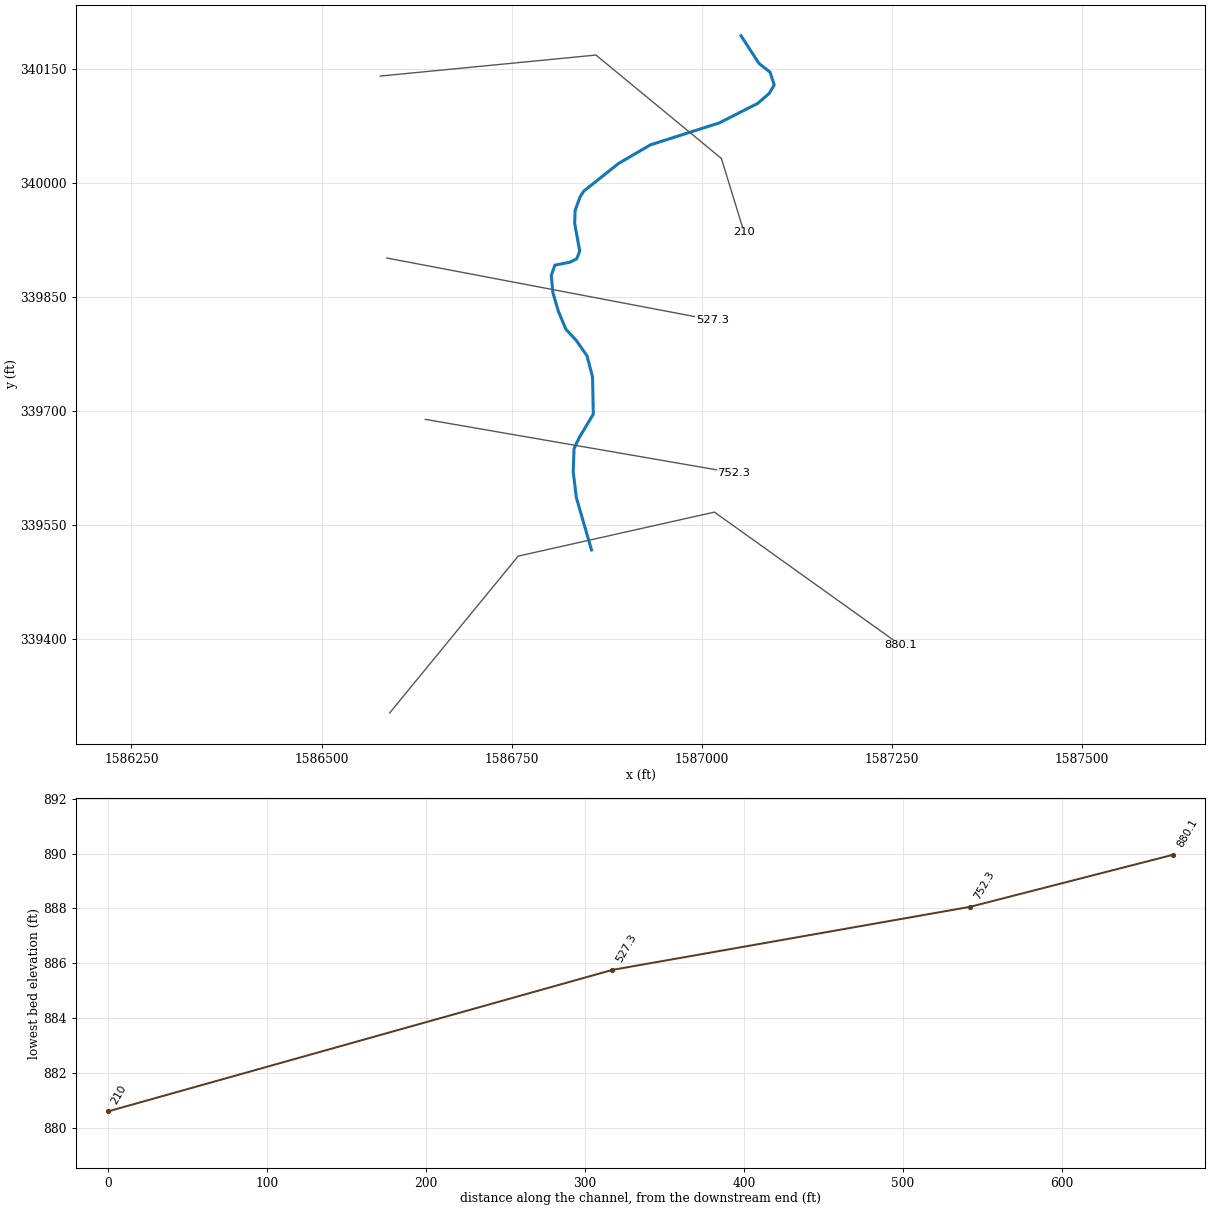
--- jcksfrk.prj (project) ---

Proj Title=jcksfrk
Current Plan=p01
Default Exp/Contr=0,0
English Units
Geom File=g01
Flow File=f01
Plan File=p01
BEGIN DESCRIPTION:
END DESCRIPTION:
DSS Export Rating Curves= 0
DSS Export Rating Curve Sorted= 0
DSS Export Volume Flow Curves= 0
DXF OffsetX= 0
DXF OffsetY= 0
DXF ScaleX= 0
DXF ScaleY= 0

--- jcksfrk.p01 (plan) ---

Plan Title=Approximate Study - 100yr
Program Version=4.00
Geom File=g01
Flow File=f01
Subcritical Flow
K Sum by GR= 0
Std Step Tol= 0.01
Critical Tol= 0.01
Num of Std Step Trials= 20
Max Error Tol= 0.3
Flow Tol Ratio= 0.001
Split Flow NTrial= 30
Split Flow Tol= 0.02
Split Flow Ratio= 0.02
Log Output Level= 0
Friction Slope Method= 1
Unsteady Friction Slope Method= 2
Unsteady Bridges Friction Slope Method= 1
Parabolic Critical Depth
Global Vel Dist= 0 , 0 , 0
Global Log Level= 0
CheckData=True
Encroach Param=-1 ,0,0, 0
Run HTab= 0
Run UNet= 0
Run PostProcess= 0
Run WQNet= 0
UNET Theta= 0
UNET Theta Warmup= 0
UNET ZTol= 0
UNET ZSATol= 0
UNET MxIter= 0
UNET MaxInSteps= 0
UNET DtIC= 0
UNET DtMin= 0
UNET MaxCRTS= 0
UNET WFStab= 0
UNET SFStab= 0
UNET WFX= 1
UNET SFX= 1
UNET DSS MLevel= 1
UNET DZMax Abort= 0
UNET Convert EG Bridges= 0
UNET Use Existing IB Tables= 0
UNET Froude Reduction=False
UNET Froude Limit= 0
UNET Froude Power= 0
UNET Time Slicing=0,0, 5
Write IC File= 0
Echo Input=False
Echo Output=False
Write Detailed= 0
Detailed Automatic Start=False, 0
WQ ULTIMATE=-1
WQ Max Comp Step=1HOUR
WQ Output Interval=15MIN
WQ Output Selected Increments= 0
WQ Output face flow=0
WQ Output face velocity=0
WQ Output face area=0
WQ Output face dispersion=0
WQ Output cell volume=0
WQ Output cell surface area=0
WQ Output cell continuity=0
WQ Output face conc=0
WQ Output face dconc_dx=0
WQ Output face courant=0
WQ Output face peclet=0
WQ Output face adv mass=0
WQ Output face disp mass=0
WQ Output cell mass=0
WQ Output cell source sink temp=0
WQ Output cell source sink nsm=0
WQ Output MaxMinRange=-1
WQ Daily Max Min Mean=-1
WQ Daily Range=0
WQ Daily Time=0
WQ Create Restart=0
WQ Fixed Restart=0
WQ System Summary=False
Sorting and Armoring Iterations= 10
XS Update Threshold= 0.02
Hydraulics Update Threshold= 0.02
Energy Slope Method= 1
Volume Change Method= 0
XS Weighting Method= 0
Number of US Weighted Cross Sections= 1
Number of DS Weighted Cross Sections= 1
Upstream XS Weight=0.25
Main XS Weight=0.5
Downstream XS Weight=0.25
Number of DS XS's Weighted with US Boundary= 1
Upstream Boundary Weight= 1
Weight of XSs Associated with US Boundary= 0
Number of US XS's Weighted with DS Boundary= 1
Downstream Boundary Weight= 0.5
Weight of XSs Associated with DS Boundary= 0.5
Sediment Output Level= 4
Mass or Volume Output= 0
Output Increment Type= 1
Profile and TS Output Increment= 10
XS Output Flag= 0
XS Output Increment= 10
Disregard all LS=0
Disregard all Conn=0
Disregard all Breaches=0
Disregard all Pumps=0

--- jcksfrk.f01 (steady flow) ---

Flow Title=USGS Regression Equation
Program Version=4.00
Number of Profiles= 1
Profile Names=P100yr
River Rch & RM=jcksfrk,Main            ,880.1
     355
River Rch & RM=jcksfrk,Main            ,210
     360
Boundary for River Rch & Prof#=jcksfrk,Main            , 1
Up Type= 0
Dn Type= 3
Dn Slope=0.013795
DSS Import GetInterval= 0
DSS Import GetPeak= 0
DSS Import FillOption= 0

--- jcksfrk.g01 (geometry) ---

Geom Title=USGS 3m DEM
Program Version=4.00

River Reach=jcksfrk         ,Main
Reach XY= 30
     1586854.993      339516.953     1586835.038      339585.917
     1586830.927      339619.675     1586832.038      339650.123
     1586839.319      339665.525     1586857.348      339695.487
     1586856.355      339744.462     1586849.063      339772.221
     1586835.083      339792.262     1586821.273      339807.233
     1586811.502      339830.693     1586804.258      339855.094
     1586802.069      339877.896     1586806.906      339891.502
     1586826.302      339895.254     1586835.505      339899.701
      1586839.52      339909.961      1586832.88      339946.136
     1586833.412        339963.1     1586839.809      339980.957
     1586844.707      339988.701     1586890.489      340025.104
     1586932.329      340049.598     1587023.073      340078.522
     1587073.733      340104.294     1587088.667      340117.268
     1587095.209      340128.407     1587089.791      340145.212
     1587075.207      340156.775      1587051.64       340193.08

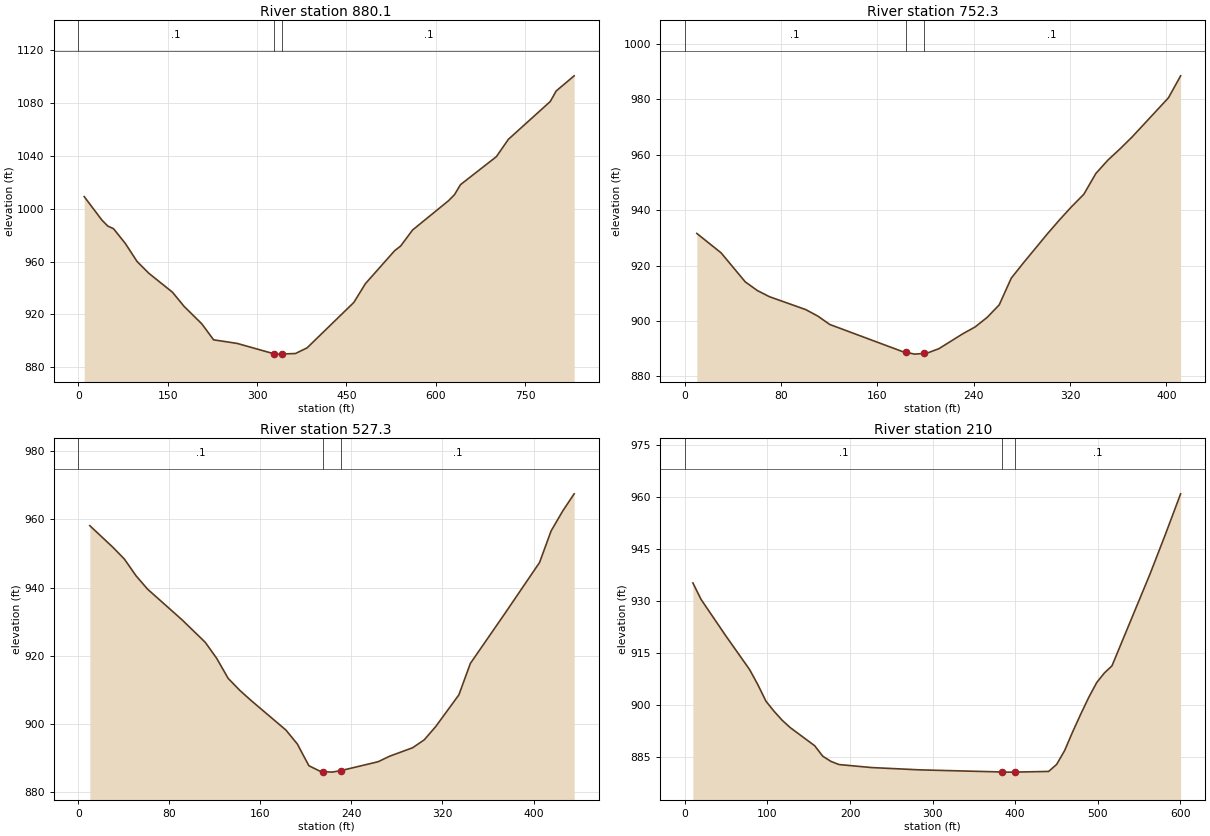
Type RM Length L Ch R = 1 ,880.1   ,136.7,127.8,119
XS GIS Cut Line= 4
     1586589.612      339302.587     1586758.545      339508.812
     1587016.638      339566.689     1587261.854      339391.397
#Sta/Elev= 30
     9.9 1009.22    39.5   991.5    49.4  986.95    59.2   984.9      79   973.7
    98.7  960.07   118.5  951.14     158  936.87   177.7  926.06   207.3  912.91
   227.1   900.8   266.6  898.08   327.7  890.32   335.2  889.96   342.7  890.06
   364.5  890.42   384.1  894.71   462.5  929.07   482.1  943.37   531.1  968.28
   541.1  971.78   561.2  983.95   621.5  1006.1   631.6 1010.72   641.6 1018.27
   701.9 1039.48     722 1052.58   792.3 1081.21   802.4 1089.25   832.5 1100.69
#Mann= 3 , 0 , 0
       0      .1       0   327.7    .045       0   342.7      .1       0
Bank Sta=327.7,342.7
XS Rating Curve= 0 ,0
Exp/Cntr=0.3,0.1

Type RM Length L Ch R = 1 ,752.3   ,225.4,225,224.1
XS GIS Cut Line= 2
     1586636.484      339688.663     1587042.296      339618.355
#Sta/Elev= 30
      10  931.57    30.1   924.6    50.2  914.12    60.3  910.98    70.3  908.77
   100.5  904.11   110.5  901.78   120.5  898.74   180.8  888.99   183.4  888.75
   190.9  888.06   198.4  888.29   200.9  888.37     211     890     231  895.41
   241.1  897.84   251.1  901.27   261.2  905.82   271.2  915.45   281.3  920.96
   301.4  931.52   311.4  936.52   321.4  941.26   331.5  945.71   341.5   953.2
   351.6  958.06   361.6  962.08   371.7   966.4   401.8  980.48   411.9   988.4
#Mann= 3 , 0 , 0
       0      .1       0   183.4    .045       0   198.4      .1       0
Bank Sta=183.4,198.4
XS Rating Curve= 0 ,0
Exp/Cntr=0.3,0.1

Type RM Length L Ch R = 1 ,527.3   ,326.4,317.3,305.2
XS GIS Cut Line= 2
     1586585.912       339900.82     1587013.926      339819.411
#Sta/Elev= 30
    10.1  958.16    30.4  951.81    40.5  948.34    50.7  943.45    60.8  939.53
    91.2  930.49   111.5  923.91   121.6  919.18   131.7  913.29   141.9  909.78
     152  906.75   182.4  898.13   192.5     894   202.6  887.64   212.8  885.96
   215.4  885.91   222.9  885.76   230.4  886.18   263.4  888.81   273.6  890.44
   293.8  892.93     304  895.26   314.1  899.17   334.4  908.46   344.5   917.7
   374.9   932.4   405.3  947.35   415.4  956.59   425.6  962.45   435.7  967.52
#Mann= 3 , 0 , 0
       0      .1       0   215.4    .045       0   230.4      .1       0
Bank Sta=215.4,230.4
XS Rating Curve= 0 ,0
Exp/Cntr=0.3,0.1

Type RM Length L Ch R = 1 ,210     ,181.3,210,238.4
XS GIS Cut Line= 4
     1586577.278      340140.113     1586860.874      340167.731
     1587025.799      340031.758     1587055.613      339934.733
#Sta/Elev= 30
     9.8  935.22    19.7  930.47    49.1  920.14    78.6  910.16    88.4  905.86
    98.3  901.06   108.1  898.16   117.9  895.57   127.7  893.44   157.2  888.23
     167   885.2   176.9   883.7   186.7  882.79     226  881.92   284.9  881.25
   384.3  880.64   391.8   880.6   399.3  880.61   440.4   880.8   450.1  882.82
   459.8  886.83   469.5  892.23   479.3  897.35     489  902.19   498.7  906.49
   507.9  909.23   517.1  911.29   563.3  937.89   581.7   949.2   600.2  960.95
#Mann= 3 , 0 , 0
       0      .1       0   384.3    .045       0   399.3      .1       0
Bank Sta=384.3,399.3
XS Rating Curve= 0 ,0
Exp/Cntr=0.3,0.1

Chan Stop Cuts=-1
Use User Specified Reach Order=0